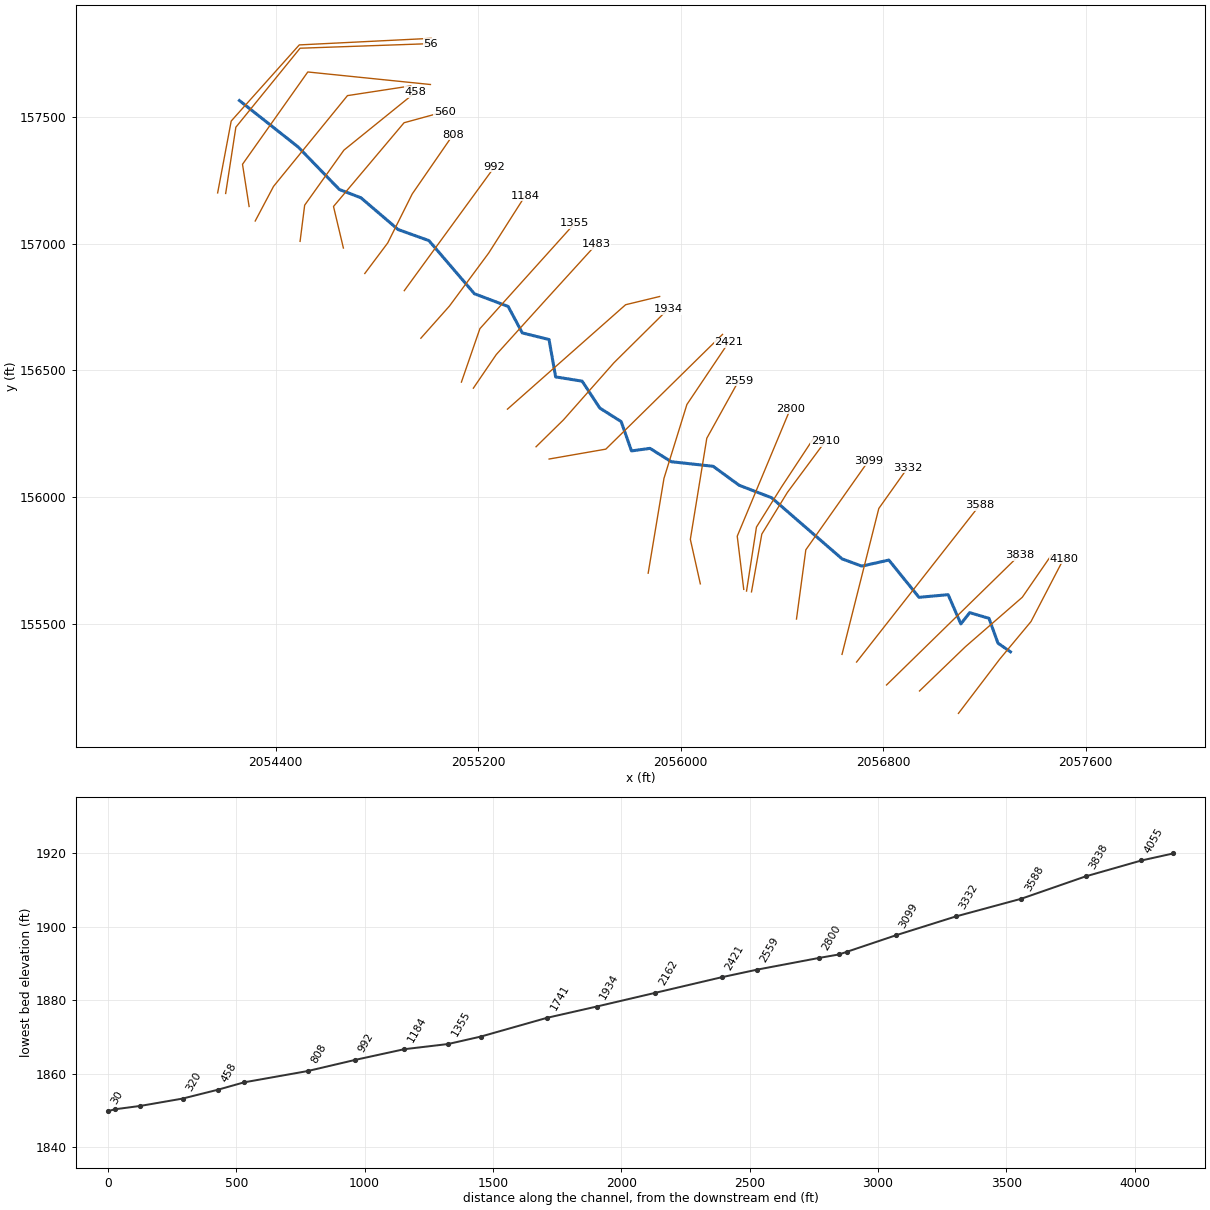
--- PNTRRN.prj (project) ---

Proj Title=PNTRRN
Current Plan=p01
Default Exp/Contr=0,0
English Units
Geom File=g01
Flow File=f01
Plan File=p01
Background Map Layer=Inundation Boundary (01pct Value_0)
BEGIN DESCRIPTION:
Stream Name: Painter Run
Flood Zone: Approximate
Monroe County, West Virginia
HEC-RAS Version: 5.0.7
Vertical Datum: NAVD88
Projection: NAD 1983 StatePlane West Virginia S FIPS 4702 (US Feet)
LiDAR: 2016, 1-meter
Land Use: 2016 NLCD
Hydrology Method:
Regression.
Model Notes: Portion of stream is in karst
END DESCRIPTION:
DSS File=dss
DSS Export Rating Curves= 0
DSS Export Rating Curve Sorted= 0
DSS Export Volume Flow Curves= 0
DXF OffsetX= 0
DXF OffsetY= 0
DXF ScaleX= 0
DXF ScaleY= 0

--- PNTRRN.p01 (plan) ---

Plan Title=Floodplain
Program Version=5.07
Short Identifier=Floodplain
Geom File=g01
Flow File=f01
Subcritical Flow
K Sum by GR= 0
Std Step Tol= 0.01
Critical Tol= 0.01
Num of Std Step Trials= 20
Max Error Tol= 0.3
Flow Tol Ratio= 0.001
Split Flow NTrial= 30
Split Flow Tol= 0.02
Split Flow Ratio= 0.02
Log Output Level= 0
Friction Slope Method= 1
Unsteady Friction Slope Method= 2
Unsteady Bridges Friction Slope Method= 1
Parabolic Critical Depth
Global Vel Dist= 0 , 0 , 0
Global Log Level= 0
CheckData=True
Encroach Param=-1 ,0,0, 0
Computation Interval=0.1SEC
Output Interval=1MIN
Instantaneous Interval=Max Profile
Mapping Interval=1HOUR
Computation Time Step Use Courant=        0
Computation Time Step Use Time Series=    0
Computation Time Step Count To Double=0
Computation Time Step Max Doubling=0
Computation Time Step Max Halving=0
Computation Time Step Residence Courant=0
Run HTab= 0
Run UNet= 0
Run Sediment= 0
Run PostProcess= 0
Run WQNet= 0
Run RASMapper=-1
UNET Theta= 0
UNET Theta Warmup= 0
UNET ZTol= 0
UNET ZSATol= 0
UNET MxIter= 0
UNET Max Iter WO Improvement= 0
UNET MaxInSteps= 0
UNET DtIC= 0
UNET DtMin= 0
UNET MaxCRTS= 0
UNET WFStab= 0
UNET SFStab= 0
UNET WFX= 1
UNET SFX= 1
UNET 1D Methodology=Finite Difference
UNET DSS MLevel= 1
UNET Pardiso=0
UNET DZMax Abort= 0
UNET Use Existing IB Tables= 0
UNET Froude Reduction=False
UNET Froude Limit= 0
UNET Froude Power= 0
UNET D1 Cores= 0
UNET D2 Coriolis=0
UNET D2 Cores= 0
UNET D2 Theta= 1
UNET D2 Theta Warmup= 1
UNET D2 Z Tol= 0.01
UNET D2 Volume Tol= 0.01
UNET D2 Max Iterations= 20
UNET D2 Equation= 0
UNET D2 RampUpFraction=0.1
UNET D2 TimeSlices= 1
UNET D2 BCVolumeCheck=0
UNET D1D2 MaxIter= 0
UNET D1D2 ZTol=0.01
UNET D1D2 QTol=0.1
UNET D1D2 MinQTol=1
DSS File=dss
Write IC File= 0
Write IC File at Fixed DateTime=0
Write IC File at Sim End=0
Echo Input=False
Echo Parameters=False
Echo Output=False
Write Detailed= 0
HDF Write Warmup=0
HDF Write Time Slices=0
HDF Flush=0
HDF Face Node Velocities=0
HDF Compression= 1
HDF Chunk Size= 1
HDF Spatial Parts= 1
HDF Use Max Rows=0
HDF Fixed Rows= 1
Calibration Method= 0
Calibration Iterations= 20
Calibration Max Change=0.05
Calibration Tolerance=0.2
Calibration Maximum=1.5
Calibration Minimum=0.5
Calibration Optimization Method= 1
WQ AD Non Conservative
WQ ULTIMATE=-1
WQ Max Comp Step=1HOUR
WQ Output Interval=15MIN
WQ Output Selected Increments= 0
WQ Output face flow=0
WQ Output face velocity=0
WQ Output face area=0
WQ Output face dispersion=0
WQ Output cell volume=0
WQ Output cell surface area=0
WQ Output cell continuity=0
WQ Output cumulative cell continuity=0
WQ Output face conc=0
WQ Output face dconc_dx=0
WQ Output face courant=0
WQ Output face peclet=0
WQ Output face adv mass=0
WQ Output face disp mass=0
WQ Output cell mass=0
WQ Output cell source sink temp=0
WQ Output nsm pathways=0
WQ Output nsm derived pathways=0
WQ Output MaxMinRange=-1
WQ Daily Max Min Mean=-1
WQ Daily Range=0
WQ Daily Time=0
WQ Create Restart=0
WQ Fixed Restart=0
WQ System Summary=0
WQ Write To DSS=0
WQ Use Fixed Temperature=0
Sorting and Armoring Iterations= 10
XS Update Threshold= 0.02
Bed Roughness Predictor= 0
Hydraulics Update Threshold= 0.02
Energy Slope Method= 1
Volume Change Method= 1
Sediment Retention Method= 0
XS Weighting Method= 0
Number of US Weighted Cross Sections= 1
Number of DS Weighted Cross Sections= 1
Upstream XS Weight=0
Main XS Weight=1
Downstream XS Weight=0
Number of DS XS's Weighted with US Boundary= 1
Upstream Boundary Weight= 1
Weight of XSs Associated with US Boundary= 0
Number of US XS's Weighted with DS Boundary= 1
Downstream Boundary Weight= 0.5
Weight of XSs Associated with DS Boundary= 0.5
Percentile Method= 0
Sediment Output Level= 3
Mass or Volume Output= 0
Output Increment Type= 1
Profile and TS Output Increment= 1
XS Output Flag= 0
XS Output Increment= 10
Write Gradation File= 0
Read Gradation Hotstart= 0
Write HDF5 File= 1
Write Binary Output= 1
Write DSS Sediment File= 0
SV Curve= 0
Specific Gage Flag= 0

--- PNTRRN.f01 (steady flow) ---

Flow Title=Flow
Program Version=5.07
Number of Profiles= 6
Profile Names=01pct,10pct,04pct,02pct,0_2pct,01plus
River Rch & RM=PNTRRN,Main            ,4180
     592     313     416     501     826     875
River Rch & RM=PNTRRN,Main            ,3838
     603     319     424     511     842     892
River Rch & RM=PNTRRN,Main            ,2162
     816     437     578     693    1130    1210
Boundary for River Rch & Prof#=PNTRRN,Main            , 1
Up Type= 0
Dn Type= 3
Dn Slope=0.01142
DSS Import GetInterval= 0
DSS Import GetPeak= 0
DSS Import FillOption= 0

--- PNTRRN.g01 (geometry) ---

Geom Title=Geometry
Program Version=5.07

River Reach=PNTRRN          ,Main
Reach XY= 30
2057302.52441388155388.2289851462057253.05059109155422.534578369
2057217.73455723155520.4334451412057141.53195372155542.941274151
2057106.45091494 155498.587999142057056.45108713155613.964097977
2056941.32016882 155603.52559609 2056822.0762278 155750.68298465
2056715.12402825155726.7581960592056637.39713523155755.360140637
2056358.88194422155996.9511929012056231.14794771 156045.98521556
2056128.19050556156120.9981036372055962.61493583156139.132570797
2055878.88548166156191.8204433012055805.80004513156181.749051645
2055764.87248594156297.6454536342055680.41020405156351.117151231
2055611.00909613 156457.096269982055506.14710113156474.110015482
2055480.10614271156621.6789460632055374.55025147156647.721216813
2055318.64714806156752.2351153942055185.31408139156802.582127556
2055005.80000472157012.304149061 2054883.7080573157056.239100561
2054737.39798246157181.4022360592054651.93817964 157214.22500506
2054489.19506681157382.1780812292054257.29920514157565.500221148

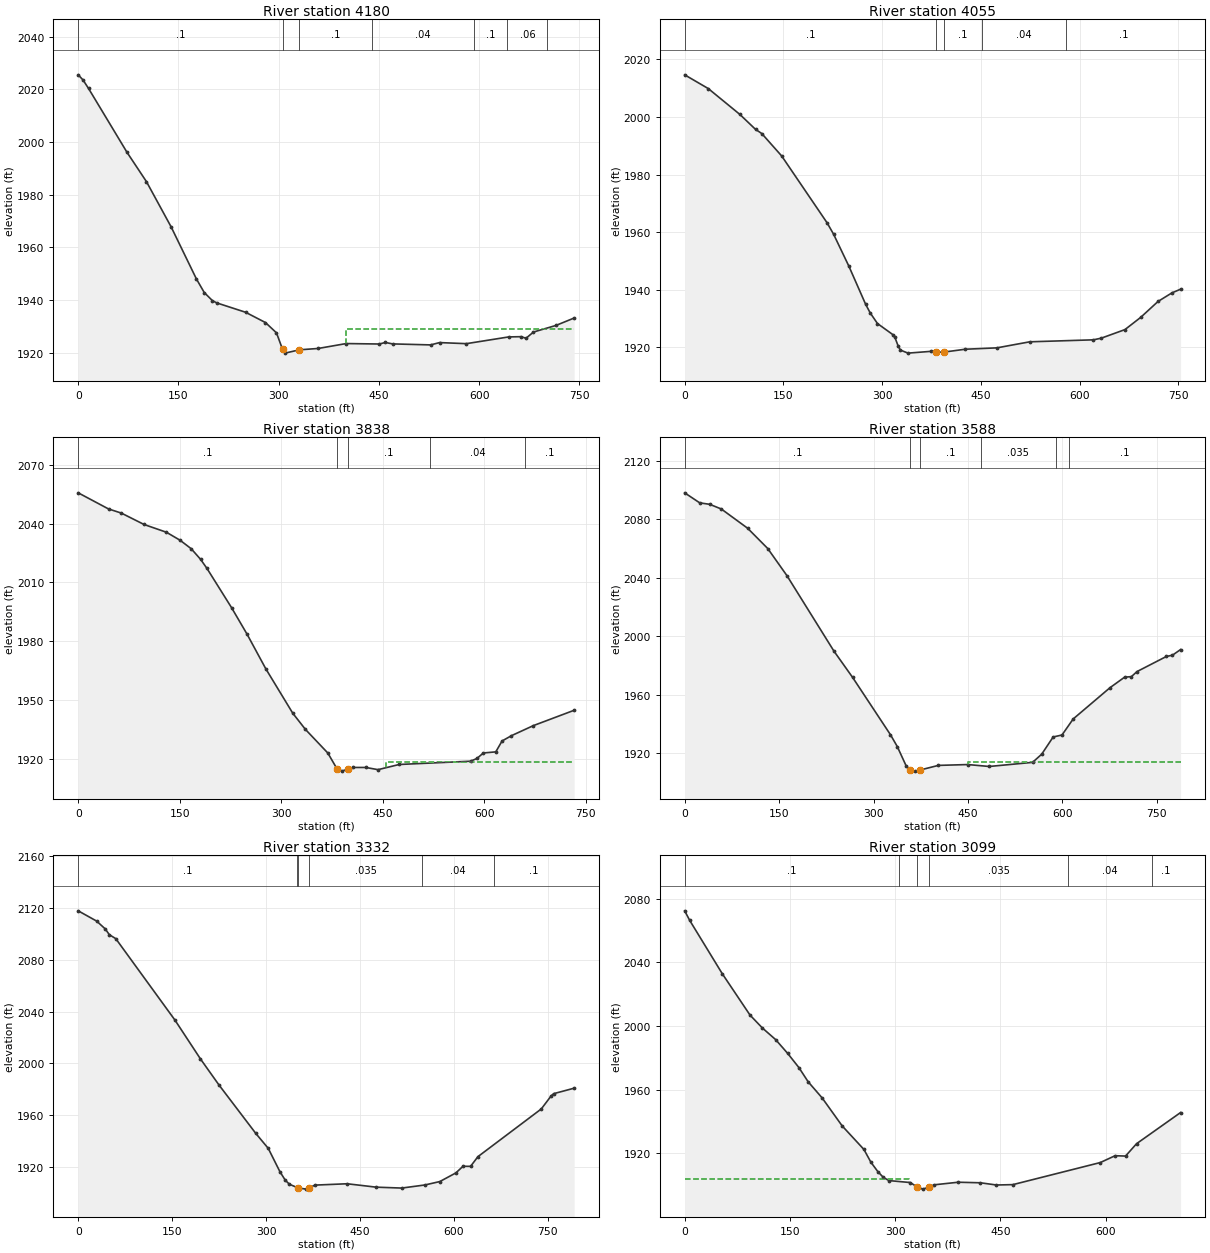
Type RM Length L Ch R = 1 ,4180    ,123.5,125.1,115.7
XS GIS Cut Line= 4
2057097.06400914 155145.171140712057259.90079904155359.117288016
2057383.51412859155507.6910014232057512.71382977155756.106250239
#Sta/Elev= 30
       0 2025.49     7.2 2023.54    15.4 2020.34    73.1 1996.05   102.1 1984.97
   139.1 1967.77   176.9 1948.03   188.6 1942.89   200.9  1939.8   207.4 1938.95
   250.4 1935.41   280.2  1931.5   296.7 1927.59   305.8 1921.28   309.5  1919.9
   330.8 1921.15   359.1 1921.67     401 1923.53   450.4 1923.36   459.7 1923.94
   470.4  1923.4   527.3 1923.02   540.7  1923.9   580.8 1923.49   644.2 1926.05
   662.7 1926.14   670.1 1925.54   681.2  1927.9   714.8  1930.4   742.1 1933.22
#Mann= 7 ,-1 , 0
       0      .1       0   305.8    .045       0   330.8      .1       0
  438.87     .04       0  592.14      .1       0  642.14     .06       0
  702.14      .1       0
#XS Ineff= 2 , 0
                          401.15          1929.1
Permanent Ineff=
       F       F
Bank Sta=305.8,330.8
XS Rating Curve= 0 ,0
Exp/Cntr(USF)=0,0
Exp/Cntr=0.3,0.1

Type RM Length L Ch R = 1 ,4055    ,160.1,217.2,147.8
XS GIS Cut Line= 4
2056943.26474016155233.6892803492057124.24341987155408.146205831
2057349.24394058155603.7988325392057465.00507805155771.734003797
#Sta/Elev= 30
       0 2014.62    35.9 2009.84    83.9 2000.86   107.6 1995.69   117.1 1994.24
   147.3 1986.46   216.3 1963.25   226.2 1959.29   249.4  1948.2   274.9 1934.95
   281.9 1931.93   292.9 1928.25   316.8 1924.31   319.3  1923.5   324.3 1920.47
   327.7 1919.04   339.3 1917.97   374.3 1918.59   381.9 1918.31   394.3 1918.34
   426.1 1919.32   474.3  1919.8   524.3  1921.9     621 1922.59     633 1923.17
   668.9 1926.14   692.8 1930.38   719.2 1935.92   740.4 1938.91   753.5 1940.17
#Mann= 5 ,-1 , 0
       0      .1       0   381.9    .045       0   394.3      .1       0
  451.37     .04       0  579.54      .1       0
Bank Sta=381.9,394.3
XS Rating Curve= 0 ,0
Exp/Cntr(USF)=0,0
Exp/Cntr=0.3,0.1

Type RM Length L Ch R = 1 ,3838    ,242.5,250.5,249.6
XS GIS Cut Line= 2
     2056813.093      155257.328     2057337.167      155769.513
#Sta/Elev= 30
       0 2055.67    44.8 2047.44    63.6 2045.35    97.3 2039.51   130.3 2035.56
   150.7 2031.43   166.9 2027.16   180.8 2021.73   190.3 2017.06   226.6 1997.05
   249.5 1983.52   277.1 1965.91   317.1 1943.15   335.8 1934.91   368.8 1922.89
   382.8 1914.56   389.6 1913.64   398.11914.646   405.5 1915.51     425 1915.51
     443 1914.39   474.3 1917.03   579.8  1918.7   589.2 1920.12   598.7 1922.91
     617 1923.47   626.3 1929.03   640.2 1931.74   672.7 1936.89   732.8  1944.7
#Mann= 5 ,-1 , 0
       0      .1       0   382.8    .045       0   398.1      .1       0
     520     .04       0     660      .1       0
#XS Ineff= 2 , 0
                          455.34         1918.31
Permanent Ineff=
       F       F
Bank Sta=382.8,398.1
XS Rating Curve= 0 ,0
Exp/Cntr=0.3,0.1

Type RM Length L Ch R = 1 ,3588    ,247.4,255.4,270.1
XS GIS Cut Line= 2
     2056694.663      155347.898     2057180.917      155967.429
#Sta/Elev= 30
       0 2098.25    23.9 2091.38    39.8 2090.37    58.2 2087.17    99.9 2074.01
   131.9  2060.1   162.3 2041.56     237 1989.82   266.7 1971.77   326.8 1932.51
   337.6 1924.43   351.5 1911.37  357.561908.378   365.5 1907.56  374.461908.392
   402.9 1911.49   449.7 1912.06   483.6 1910.75   552.5 1913.56     567 1919.18
   585.2 1930.96   599.2 1932.31     617 1943.31   675.4 1964.71   698.7 1971.96
   709.4 1972.29   718.4 1975.79   765.1 1986.15   774.5 1986.96   787.6 1990.88
#Mann= 6 ,-1 , 0
       0      .1       0  357.56    .045       0  374.46      .1       0
     470    .035       0     590     .04       0     610      .1       0
#XS Ineff= 2 , 0
                          450.68         1913.72
Permanent Ineff=
       F       F
Bank Sta=357.56,374.46
XS Rating Curve= 0 ,0
Exp/Cntr=0.3,0.1

Type RM Length L Ch R = 1 ,3332    ,240.8,233.1,220.4
XS GIS Cut Line= 3
       2056637.2      155378.125     2056782.479      155954.409
     2056897.062      156115.867
#Sta/Elev= 30
       0 2117.85    29.5  2109.9    43.1  2103.9    49.8 2099.37      60 2096.35
   154.7 2033.28   195.3 2003.37   224.9 1983.22   283.7  1945.8   303.6 1934.24
   322.2 1916.25   330.7  1909.7   337.4  1906.5  351.571903.602   364.5 1902.73
     3691903.642     378 1905.83   429.6 1906.88   476.2 1904.24   516.8 1903.55
     554 1905.95   577.7 1908.59   603.3 1915.25   614.7 1920.38   626.8 1920.33
   638.6 1927.84   739.8 1964.71   755.6 1974.82   759.6 1976.52   792.3 1980.76
#Mann= 6 ,-1 , 0
       0      .1       0     350    .035       0  351.57    .045       0
     369    .035       0     550     .04       0  664.31      .1       0
Bank Sta=351.57,369
XS Rating Curve= 0 ,0
Exp/Cntr=0.3,0.1

Type RM Length L Ch R = 1 ,3099    ,187,188.8,190.6
XS GIS Cut Line= 3
     2056457.392      155517.777     2056494.285      155791.214
     2056742.559       156143.56
#Sta/Elev= 30
       0 2072.27     7.2 2066.24    53.5 2032.86    93.2  2006.8   110.8 1998.72
   129.7 1991.43   146.8  1982.8   162.8  1973.9     176 1964.98   195.9 1954.87
   224.5 1937.28   255.5 1922.51   265.4 1914.52   275.3 1908.62   283.2 1904.96
   291.2 1902.97   321.6 1901.74  331.551898.911   339.4 1897.61  348.621898.923
   355.5 1900.31   389.8 1901.94   421.6 1901.59   444.3  1900.2   467.8 1900.43
   592.4 1914.29   613.5 1918.58   628.4 1918.36   644.1 1926.12   706.9  1945.7
#Mann= 6 ,-1 , 0
       0      .1       0  305.91    .035       0  331.55    .045       0
  348.62    .035       0  545.91     .04       0  665.91      .1       0
#XS Ineff= 2 , 0
          319.84 1903.69
Permanent Ineff=
       F       F
Bank Sta=331.55,348.62
XS Rating Curve= 0 ,0
Exp/Cntr=0.3,0.1

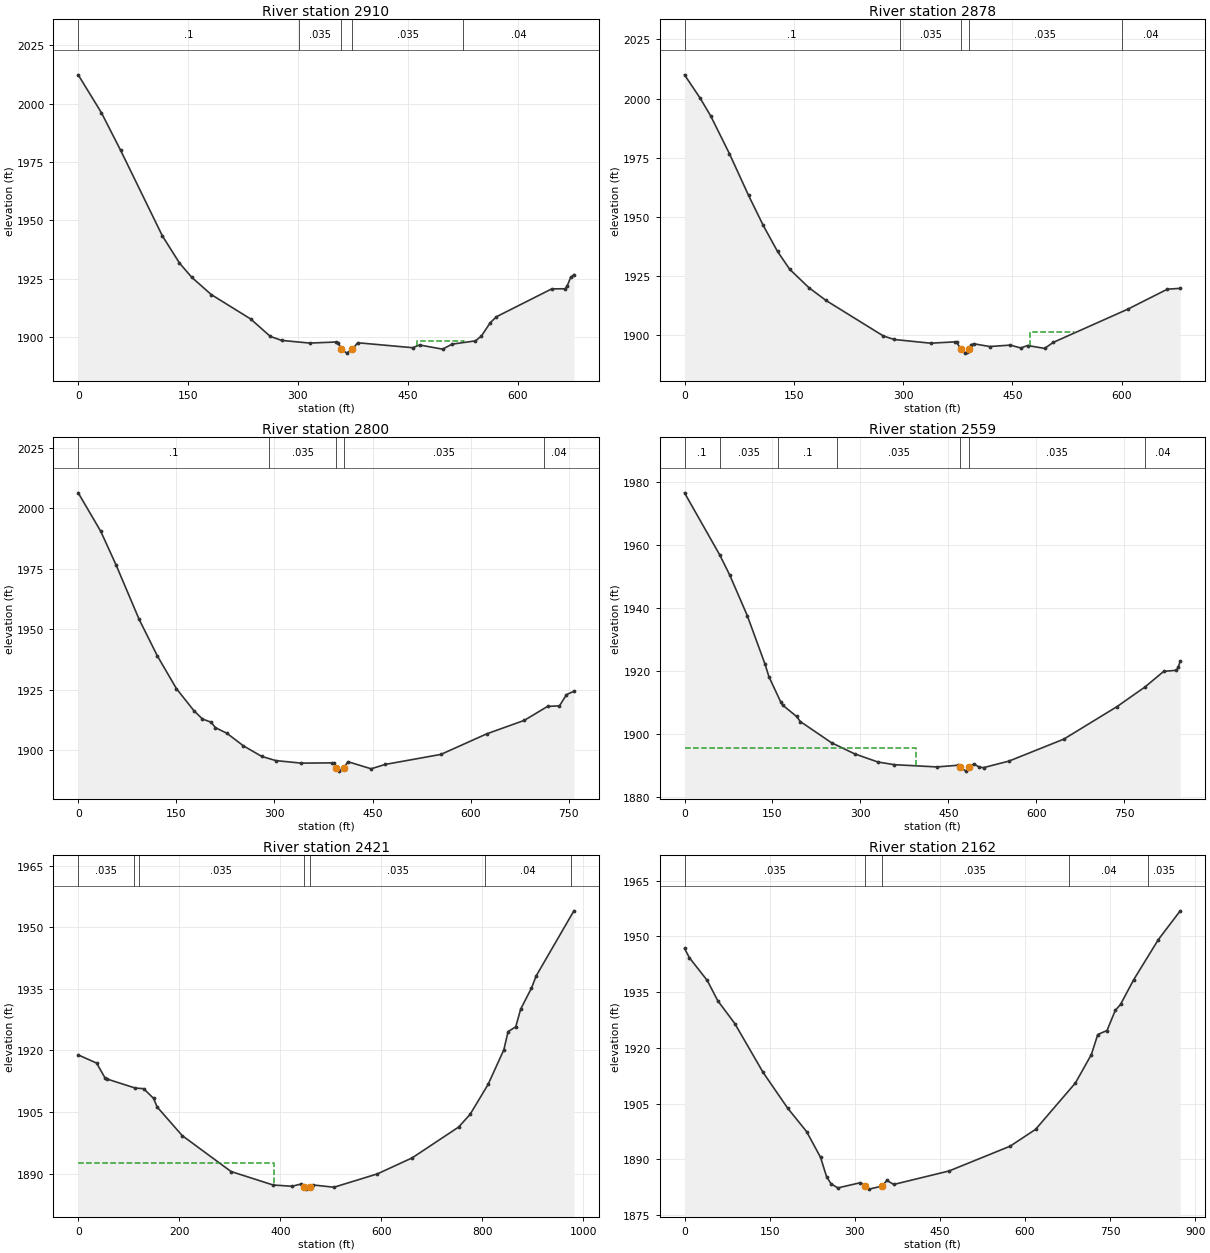
Type RM Length L Ch R = 1 ,2910    ,33.3,32.5,31.6
XS GIS Cut Line= 4
2056279.67624791155624.9945337662056320.43721181155853.255931593
2056421.52440227156017.9302257392056571.52474942156220.104606672
#Sta/Elev= 30
       0 2012.28    31.6 1996.12    57.9 1979.98   114.9 1943.37   138.3 1931.72
   154.9 1925.66   181.6 1918.25   235.4  1907.8   262.3 1900.33   277.7 1898.62
   316.2 1897.47   352.3 1897.93   354.7 1897.69   359.4 1894.95   366.6 1893.17
     374 1894.74   381.7 1897.61   456.6 1895.49   466.1 1896.65   497.5 1894.87
   510.6 1897.03   542.4 1898.41   550.5 1900.49   562.8 1906.25     571 1908.74
   646.6 1920.68     665 1920.71   667.7 1921.96   672.4 1925.62   676.8 1926.77
#Mann= 5 ,-1 , 0
       0      .1       0  301.87    .035       0   359.4    .045       0
     374    .035       0   525.1     .04       0
#XS Ineff= 3 ,-1
  334.85  349.43  1895.5   378.6  402.35 1895.46  463.18  527.351898.414
Permanent Ineff=
       F       F       F
Bank Sta=359.4,374
XS Rating Curve= 0 ,0
Exp/Cntr(USF)=0,0
Exp/Cntr=0.3,0.1

Type RM Length L Ch R = 1 ,2878    ,74.6,78,82.2
XS GIS Cut Line= 4
2056260.11098524155628.2554108782056299.24151058155880.973387043
2056397.06782393 156037.495488412056529.13334696156238.039430787
#Sta/Elev= 30
       0 2010.01    21.5 2000.13    35.8 1992.72    61.6 1976.72    87.9 1959.06
   107.9 1946.46   127.7 1935.35   144.4 1927.83   170.9 1920.02   194.2 1914.66
     273 1899.64   287.8 1898.16   337.8  1896.6   371.2 1897.16   373.6 1896.92
   379.7 1893.99   385.4  1892.4   387.8 1892.75   390.2 1893.98   392.9 1895.87
   396.8 1896.37   418.8 1895.19   447.2 1895.79   461.5 1894.59     471 1895.62
   494.3 1894.39   506.1 1896.93   608.4 1910.97   662.8 1919.42   680.4 1919.78
#Mann= 5 ,-1 , 0
       0      .1       0  295.73    .035       0   379.7    .045       0
   390.2    .035       0  600.31     .04       0
#XS Ineff= 3 ,-1
  366.88  376.36  1894.3  392.48  411.13 1894.26  474.52  534.871901.136
Permanent Ineff=
       F       F       F
Bank Sta=379.7,390.2
XS Rating Curve= 0 ,0
Exp/Cntr(USF)=0,0
Exp/Cntr=0.3,0.1

Type RM Length L Ch R = 1 ,2800    ,231.1,240.8,245
XS GIS Cut Line= 3
     2056249.059      155634.964     2056223.371       155844.96
     2056433.521       156348.94
#Sta/Elev= 30
       0 2006.37    34.5 1990.46    57.7  1976.7    93.2 1954.08   121.1 1938.97
   150.2 1925.49   176.7 1916.47   189.9 1912.97   203.1 1911.66   209.7 1909.41
   227.3 1907.08   252.2 1901.95   280.4 1897.54     302  1895.8     341 1894.75
   388.6 1894.87   390.9 1894.73   394.71892.763   398.7 1891.45  406.341892.866
   412.2 1895.35   447.7 1892.41   469.1 1894.21   554.4 1898.36   624.4 1906.85
   681.7  1912.4   717.3 1918.17   735.6 1918.42   746.3 1923.04   757.6 1924.43
#Mann= 5 ,-1 , 0
       0      .1       0  291.56    .035       0   394.7    .045       0
  406.34    .035       0  711.56     .04       0
Bank Sta=394.7,406.34
XS Rating Curve= 0 ,0
Exp/Cntr=0.3,0.1

Type RM Length L Ch R = 1 ,2559    ,140.4,137.7,135.1
XS GIS Cut Line= 4
     2056077.618      155656.666     2056038.158      155832.538
     2056103.169      156231.832     2056229.528      156459.617
#Sta/Elev= 30
       0 1976.44      60 1956.79    76.8 1950.52     107 1937.55   137.3 1922.17
     144 1918.16   164.2 1910.13   167.5 1909.16     191 1905.61   197.6 1903.97
   250.8 1897.25   289.9 1893.76   329.6 1891.17   357.4 1890.32   430.3  1889.6
   466.9 1890.14   470.2 1889.44   480.2 1888.27   485.6 1889.46   493.4 1890.59
   502.8 1889.51   510.1 1889.39   553.3 1891.45   646.8 1898.41   737.6 1908.72
   784.8 1914.87   817.2 1919.88   838.9 1920.21   841.9 1921.12   845.3 1923.14
#Mann= 7 ,-1 , 0
       0      .1       0      60    .035       0     160      .1       0
  260.24    .035       0   470.2    .045       0   485.6    .035       0
   784.8     .04       0
#XS Ineff= 2 , 0
          393.98 1895.49
Permanent Ineff=
       F       F
Bank Sta=470.2,485.6
XS Rating Curve= 0 ,0
Exp/Cntr=0.3,0.1

Type RM Length L Ch R = 1 ,2421    ,254.9,259,225.3
XS GIS Cut Line= 4
2055871.62377377155698.9278771712055934.02327406156073.324878898
2056024.60319383156365.1935092762056189.65993653156610.765736215
#Sta/Elev= 30
       0 1918.92    36.4 1916.93      53 1913.34    56.4 1913.07   112.9 1910.84
   129.5 1910.69   149.1 1908.34   156.2 1906.24   205.9 1899.25   302.5  1890.5
   385.9 1887.21   423.6 1886.91   440.8 1887.46   446.8 1886.67   451.1 1886.21
   458.7 1886.64   463.9 1887.24   506.1 1886.67     592 1889.92     661 1893.83
   752.8 1901.33   775.6 1904.43   811.1 1911.71   842.4 1920.17   850.7 1924.58
   865.9 1925.77   875.7 1930.09     897 1935.19   906.4 1938.18     981 1954.03
#Mann= 7 ,-1 , 0
       0    .035       0     110      .1       0     120    .035       0
   446.8    .045       0   458.7    .035       0  805.16     .04       0
  975.16    .035       0
#XS Ineff= 2 , 0
          388.25 1892.55
Permanent Ineff=
       F       F
Bank Sta=446.8,458.7
XS Rating Curve= 0 ,0
Exp/Cntr(USF)=0,0
Exp/Cntr=0.3,0.1

Type RM Length L Ch R = 1 ,2162    ,213.4,228.7,217.8
XS GIS Cut Line= 3
     2055480.396      156149.721     2055704.354      156188.784
     2056165.292      156641.909
#Sta/Elev= 30
       0 1946.77     8.7 1944.26    40.1 1938.15    58.6  1932.7    88.6 1926.56
   138.6 1913.37   181.9 1903.75   215.2 1897.45   239.7 1890.54   250.5 1885.27
   258.4 1883.38   270.3 1882.29   309.9 1883.69   318.71882.816   325.5 1881.96
  348.041882.778   356.7  1884.3   368.8 1883.22   466.3 1886.85     574 1893.53
   618.8 1898.06     689 1910.55   717.1  1918.2   728.4  1923.6   744.7 1924.68
   759.2 1930.08   768.5 1931.71   791.9 1938.41   835.1 1949.15   873.7 1956.91
#Mann= 5 ,-1 , 0
       0    .035       0   318.7    .045       0  348.04    .035       0
  677.34     .04       0  817.34    .035       0
Bank Sta=318.7,348.04
XS Rating Curve= 0 ,0
Exp/Cntr=0.3,0.1

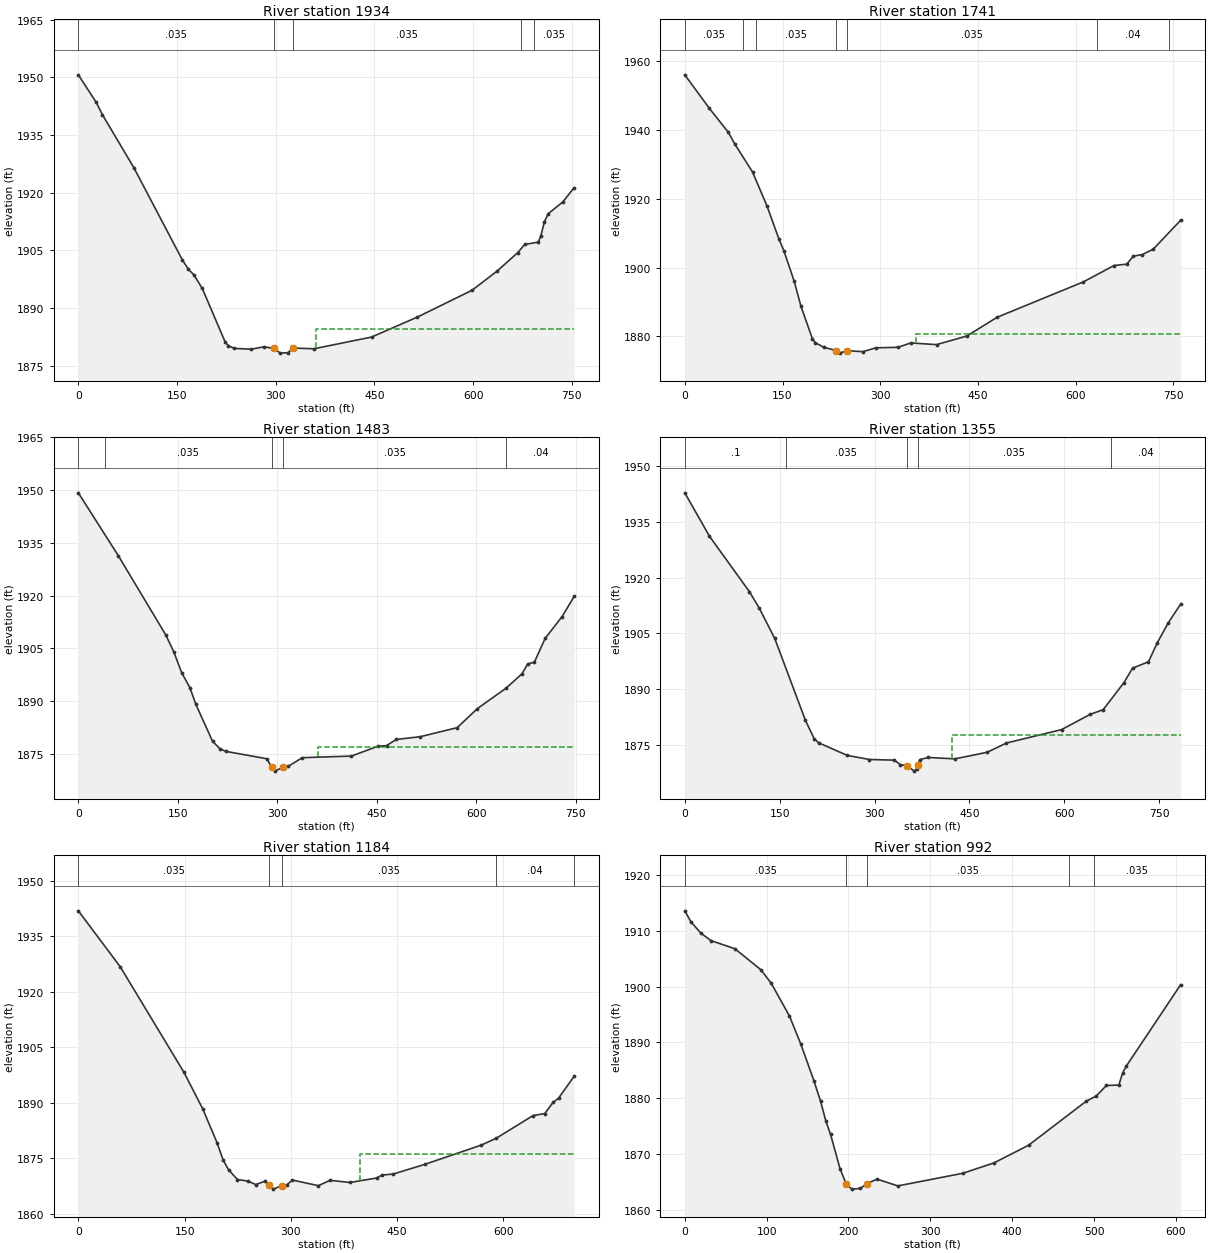
Type RM Length L Ch R = 1 ,1934    ,191,193,186.6
XS GIS Cut Line= 4
2055428.78861044156198.1238794732055537.48451416156304.806896094
2055736.76033766156530.2502519732055950.12637091156741.603398109
#Sta/Elev= 30
       0 1950.61    27.1 1943.47    36.5 1940.27    84.3 1926.48   158.3 1902.39
   167.4 1900.01   175.4 1898.63   188.3 1895.07   223.1 1881.13   227.8 1880.18
   237.1 1879.44     263 1879.25   282.1 1879.87     298 1879.43   306.8 1878.22
   318.4 1878.33   326.7 1879.54     358 1879.35   445.6  1882.4   515.4 1887.61
   598.5 1894.59   636.5 1899.58   667.8 1904.36   678.3 1906.48   699.2  1907.1
   702.9 1908.77   708.4 1912.42   713.9 1914.46   736.3 1917.55   753.5 1921.26
#Mann= 5 ,-1 , 0
       0    .035       0     298    .045       0   326.7    .035       0
  673.19     .04       0  693.19    .035       0
#XS Ineff= 2 , 0
                          360.68         1884.51
Permanent Ineff=
       F       F
Bank Sta=298,326.7
XS Rating Curve= 0 ,0
Exp/Cntr(USF)=0,0
Exp/Cntr=0.3,0.1

Type RM Length L Ch R = 1 ,1741    ,254.9,257.6,257.4
XS GIS Cut Line= 3
     2055315.899       156346.77     2055782.479      156759.096
     2055917.028      156791.648
#Sta/Elev= 30
       0 1955.96    37.7 1946.22    66.8 1939.28    76.7 1935.89     104 1927.74
   126.3 1917.84   144.6 1908.23   152.1 1904.87   167.9 1896.05   178.4  1888.7
   195.9 1879.33   200.4 1878.18   213.4 1876.85   232.71875.891   237.6 1875.16
   249.11875.878   273.2 1875.58   293.4  1876.7   327.2 1876.85   346.9 1878.12
   386.4 1877.63   432.9 1880.12   479.3 1885.56   611.8 1895.84   658.9  1900.6
   678.5    1901   688.6 1903.32   702.1 1903.76     719 1905.33   761.1 1913.73
#Mann= 7 ,-1 , 0
       0    .035       0      90      .1       0     110    .035       0
   232.7    .045       0   249.1    .035       0  632.66     .04       0
  742.66    .035       0
#XS Ineff= 2 , 0
                          354.15         1880.59
Permanent Ineff=
       F       F
Bank Sta=232.7,249.1
XS Rating Curve= 0 ,0
Exp/Cntr=0.3,0.1

Type RM Length L Ch R = 1 ,1483    ,126.2,128.2,125.4
XS GIS Cut Line= 4
2055181.20349639 156429.605896672055271.78341616156562.456445669
2055463.00769124156773.8095918052055666.30928895156997.240060578
#Sta/Elev= 30
       0 1949.25    60.5  1931.3     132 1908.78   144.1 1903.96   155.8  1898.1
   168.5 1893.72   176.9 1889.23   202.4 1878.57   214.1 1876.34   223.4 1875.65
     284 1873.59  291.481871.316   296.8 1870.06   308.4 1871.16   316.3 1871.38
   337.8 1873.89   411.9 1874.34   451.7 1877.13   464.9 1877.32   479.5 1879.07
   515.8 1879.86   571.5 1882.43   601.9 1887.85   645.2 1893.66   669.3 1897.78
   677.9 1900.57   687.9 1901.06   704.1 1907.82   729.7 1914.04   747.9 1919.78
#Mann= 5 ,-1 , 0
       0      .1       0      40    .035       0  291.48    .045       0
   308.4    .035       0  645.81     .04       0
#XS Ineff= 2 , 0
                          362.18         1877.06
Permanent Ineff=
       F       F
Bank Sta=291.48,308.4
XS Rating Curve= 0 ,0
Exp/Cntr(USF)=0,0
Exp/Cntr=0.3,0.1

Type RM Length L Ch R = 1 ,1355    ,166.7,170.9,171.5
XS GIS Cut Line= 3
     2055134.042      156453.541     2055206.958      156664.478
     2055581.958      157081.145
#Sta/Elev= 30
       0 1942.76      39  1931.1   102.2  1916.2   117.8 1911.77   142.2 1903.64
   190.7 1881.65   204.6 1876.71   211.6 1875.62   256.9 1872.24   291.9 1871.14
   331.4 1870.97   340.7 1869.77     3511869.503   362.9 1868.02   366.3 1868.64
     3681869.586   371.7 1871.13   384.9 1871.69   426.7 1871.31     478 1873.08
   508.5 1875.57   595.7 1879.18     641 1883.28   661.3 1884.51   693.9 1891.72
   707.8 1895.67     733 1897.38   746.9 1902.49   764.5 1907.91   783.8 1912.87
#Mann= 5 ,-1 , 0
       0      .1       0     160    .035       0     351    .045       0
     368    .035       0  673.18     .04       0
#XS Ineff= 2 , 0
                          422.92         1877.65
Permanent Ineff=
       F       F
Bank Sta=351,368
XS Rating Curve= 0 ,0
Exp/Cntr=0.3,0.1

Type RM Length L Ch R = 1 ,1184    ,188.9,191.6,191.1
XS GIS Cut Line= 4
2054973.87612447156626.8688330632055086.59780241156753.680720745
2055241.59010957156963.0209797752055386.51798121157190.477222759
#Sta/Elev= 30
       0 1941.87    59.2 1926.73     149 1898.23   175.6 1888.32   195.7 1879.21
   204.2 1874.56   212.1 1871.81   224.6 1869.21   239.3 1868.78   250.4 1867.85
   263.7 1868.77  269.721867.676   275.4 1866.61   287.2 1867.55   294.2 1867.77
   302.2 1869.07   338.8 1867.54   355.2 1868.99   383.3 1868.41   420.9 1869.61
   428.7 1870.41   444.5 1870.69   489.7 1873.35   568.8 1878.52   589.5 1880.33
   641.7 1886.49   658.4 1887.05     670 1890.05   677.8 1891.21   699.8 1897.12
#Mann= 5 ,-1 , 0
       0    .035       0  269.72    .045       0   287.2    .035       0
  590.14     .04       0  699.85      .1       0
#XS Ineff= 2 , 0
                          397.46         1876.12
Permanent Ineff=
       F       F
Bank Sta=269.72,287.2
XS Rating Curve= 0 ,0
Exp/Cntr(USF)=0,0
Exp/Cntr=0.3,0.1

Type RM Length L Ch R = 1 ,992     ,181.1,184.8,190.9
XS GIS Cut Line= 2
     2054908.347      156814.652     2055265.118      157304.235
#Sta/Elev= 30
       0  1913.6     7.6 1911.61    19.8 1909.57      32 1908.26    61.1 1906.81
    92.9 1903.04   105.6 1900.61   127.9 1894.73   141.6 1889.76   157.8 1883.11
   165.9 1879.44   172.5 1875.82   178.1 1873.49   189.8 1867.29  197.051864.682
   203.9 1863.69   214.6 1863.82   222.7 1864.69   234.9 1865.48   260.3 1864.27
   339.6 1866.53   377.7 1868.39     420 1871.56   490.4 1879.45   502.9 1880.41
   515.1 1882.28   530.3 1882.35     535 1884.55   539.4 1885.75   605.8 1900.35
#Mann= 5 ,-1 , 0
       0    .035       0  197.05    .045       0   222.7    .035       0
     470     .04       0     500    .035       0
Bank Sta=197.05,222.7
XS Rating Curve= 0 ,0
Exp/Cntr=0.3,0.1

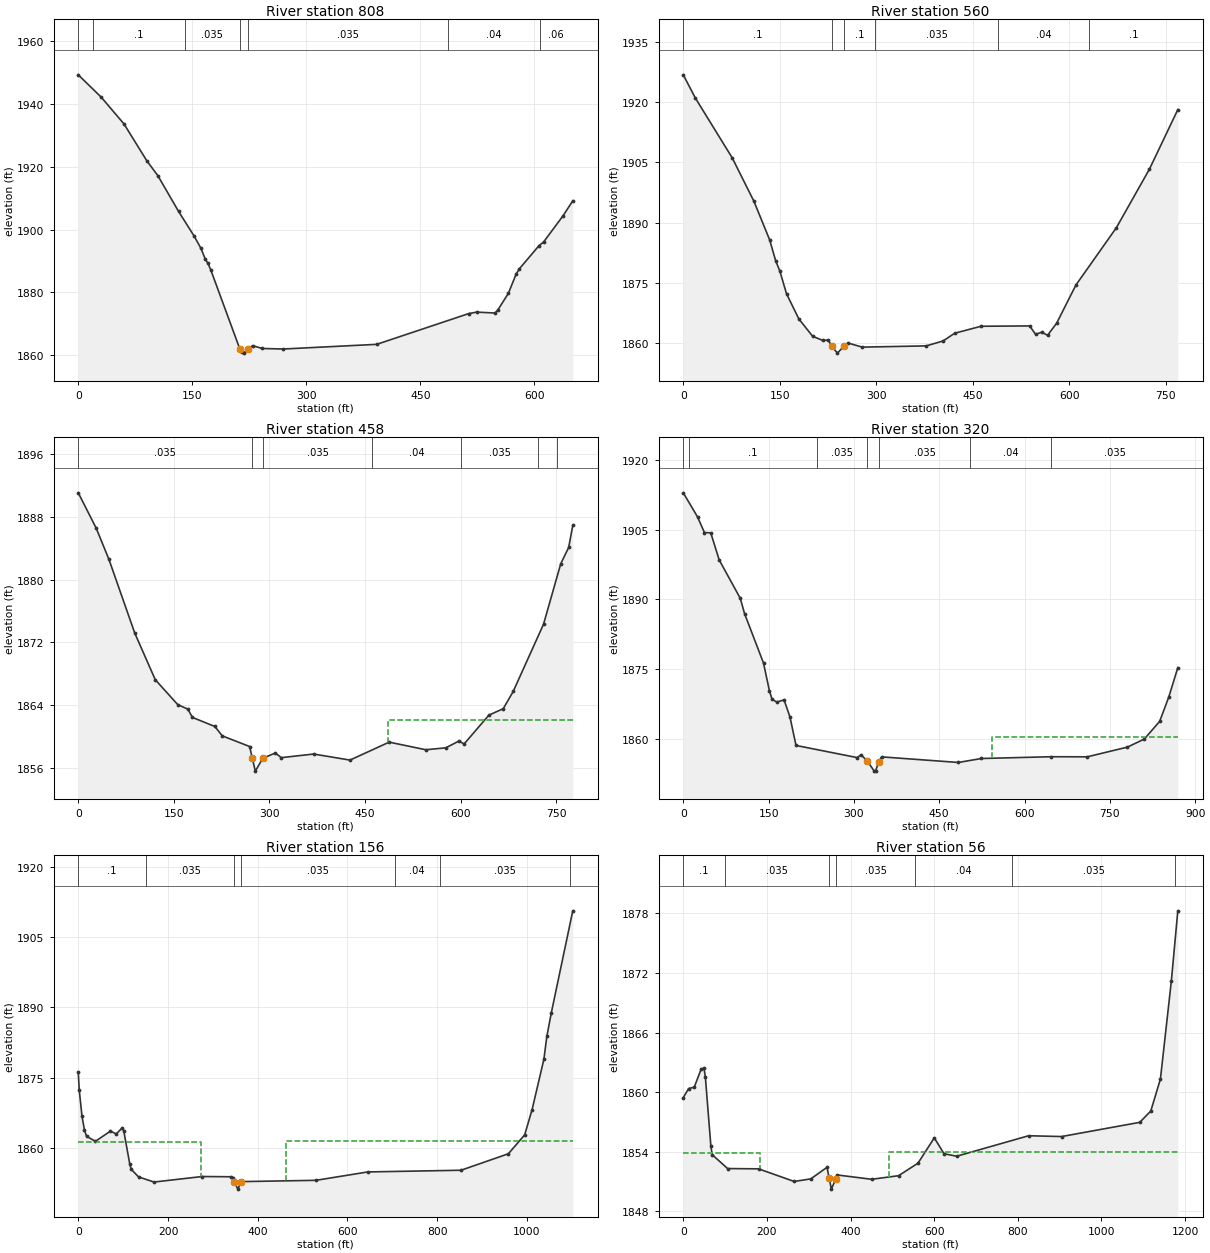
Type RM Length L Ch R = 1 ,808     ,251.8,247.4,239.6
XS GIS Cut Line= 4
 2054752.4585428156882.5054955322054843.03846257157003.278721896
2054939.65704367157196.5158840772055100.68801215 157430.01078838
#Sta/Elev= 30
       0 1949.35      30 1942.28    60.2 1933.69    90.1 1921.99   104.7 1917.23
     132 1905.81   152.4 1897.99   161.4 1894.06     167 1890.68   170.7 1889.27
   174.4 1887.15  212.761861.875   215.2 1860.91   217.6 1860.66  223.121861.873
   229.4 1863.04   242.1 1862.14   269.7 1861.97   392.7 1863.46   513.9 1873.27
   524.4 1873.73   548.4 1873.44   552.3 1874.48   565.9  1879.7   576.2 1885.85
   580.2 1887.47   606.4 1894.95   612.2 1896.05     638 1904.46   650.7 1909.21
#Mann= 7 ,-1 , 0
       0    .035       0      20      .1       0     140    .035       0
  212.76    .045       0  223.12    .035       0  487.01     .04       0
  607.01     .06       0
Bank Sta=212.76,223.12
XS Rating Curve= 0 ,0
Exp/Cntr(USF)=0,0
Exp/Cntr=0.3,0.1

Type RM Length L Ch R = 1 ,560     ,100.3,102.1,104.9
XS GIS Cut Line= 4
     2054667.896      156983.054     2054628.833      157147.117
     2054907.479      157477.846     2055068.937      157522.117
#Sta/Elev= 30
       0 1926.77    18.7 1921.01      76 1906.14   109.8 1895.33   134.3 1885.71
   143.5 1880.58   150.2 1877.91   160.4 1872.36   179.5 1866.11     201 1861.78
   216.8 1860.74   225.5 1860.85   230.7 1859.25   239.6 1857.59  249.051859.245
     256  1860.1   278.2 1859.08   377.5 1859.39   403.7 1860.61   421.7 1862.53
   462.7 1864.27   538.2 1864.35   547.5 1862.28   557.1 1862.78   566.1 1862.03
   580.1    1865   610.2 1874.53   673.1 1888.78   724.4 1903.32   768.5 1918.12
#Mann= 6 ,-1 , 0
       0      .1       0   230.7    .045       0  249.05      .1       0
  298.65    .035       0  488.65     .04       0  631.11      .1       0
Bank Sta=230.7,249.05
XS Rating Curve= 0 ,0
Exp/Cntr=0.3,0.1

Type RM Length L Ch R = 1 ,458     ,137.5,137.6,134.6
XS GIS Cut Line= 4
2054496.82188033157009.3173832142054514.93786429157152.232367744
2054669.93017145157369.6241751982054953.74725341157599.093305289
#Sta/Elev= 30
       0  1891.1    28.2 1886.58    48.1 1882.61    88.6 1873.21   120.8 1867.25
   156.1 1864.07   172.2 1863.48     179 1862.44   214.3 1861.28     226 1860.08
   268.9 1858.72   273.1 1857.23   277.8 1855.58   289.6 1857.22   309.2 1857.89
   318.6  1857.3   369.4 1857.76   426.4 1856.99   487.9 1859.28   545.3 1858.31
   576.6 1858.55   597.4 1859.42   605.5 1859.05   644.4 1862.73   666.9 1863.55
   682.5 1865.75   730.1 1874.33   757.1 1882.04   769.6 1884.14     776 1886.94
#Mann= 7 ,-1 , 0
       0    .035       0   273.1    .045       0   289.6    .035       0
  461.05     .04       0  601.05    .035       0  721.05      .1       0
  751.05    .035       0
#XS Ineff= 2 , 0
                          485.96         1862.06
Permanent Ineff=
       F       F
Bank Sta=273.1,289.6
XS Rating Curve= 0 ,0
Exp/Cntr(USF)=0,0
Exp/Cntr=0.3,0.1

Type RM Length L Ch R = 1 ,320     ,161.8,164,165.6
XS GIS Cut Line= 4
  2054319.687815157089.8328674562054392.15175082157226.709190668
 2054684.0203812157585.0030955462054933.61838235157623.247950561
#Sta/Elev= 30
       0 1912.89    25.2 1907.69    37.1 1904.37    48.3  1904.3    63.1  1898.5
   100.2 1890.25   107.7 1886.98   141.1 1876.34   151.4 1870.41   156.1 1868.58
   164.5 1867.99   177.2 1868.47   187.6 1864.77   198.2 1858.68   305.5 1856.08
   312.6 1856.67  323.611855.309   335.8 1853.17   338.3 1853.28   343.4 1855.13
   348.6 1856.23   483.7 1855.03   524.2 1855.88     647 1856.26   710.3 1856.24
   780.8 1858.32   810.6 1860.05   837.6 1863.84   853.8 1869.13   869.5 1875.38
#Mann= 7 ,-1 , 0
       0     .08       0      10      .1       0  234.87    .035       0
  323.61    .045       0   343.4    .035       0  504.87     .04       0
     647    .035       0
#XS Ineff= 2 , 0
                          542.37         1860.59
Permanent Ineff=
       F       F
Bank Sta=323.61,343.4
XS Rating Curve= 0 ,0
Exp/Cntr(USF)=0,0
Exp/Cntr=0.3,0.1

Type RM Length L Ch R = 1 ,156     ,102.2,100.7,98.6
XS GIS Cut Line= 4
       2054295.5      157147.117     2054269.458      157313.784
     2054527.271      157678.367     2055011.646      157628.888
#Sta/Elev= 30
       0 1876.12     2.2 1872.28     8.4 1866.69    13.7 1863.84    18.4 1862.46
    38.3 1861.39    71.5 1863.55    84.8 1862.97    98.1 1864.27   101.4 1863.62
   114.7 1856.58     118 1855.42   134.3 1853.79   168.7 1852.69   276.1 1853.87
   340.4 1853.82   344.4 1853.66     3481852.672   355.7 1851.18   363.21852.783
   529.8 1853.06   645.3 1854.85     853 1855.21   958.6 1858.73   994.9 1862.77
  1011.4 1868.14  1037.7  1878.9  1044.3 1883.77  1054.2 1888.79  1102.1 1910.58
#Mann= 7 ,-1 , 0
       0      .1       0     150    .035       0     348    .045       0
   363.2    .035       0  705.22     .04       0  805.22    .035       0
 1095.22      .1       0
#XS Ineff= 2 , 0
          274.43 1861.32  461.93         1861.41
Permanent Ineff=
       F       F
Bank Sta=348,363.2
XS Rating Curve= 0 ,0
Exp/Cntr=0.3,0.1

Type RM Length L Ch R = 1 ,56      ,26.8,26,24.2
XS GIS Cut Line= 4
2054202.94036285157198.5287711832054243.19810497157460.204094971
2054496.82188033157772.2015964092055012.12097948157790.317580364
#Sta/Elev= 30
       0 1859.46    12.8 1860.37    26.1  1860.5    42.7 1862.32    49.4 1862.43
    52.7 1861.57      66 1854.55    69.3 1853.71     106 1852.32   180.1 1852.29
   265.2 1851.02   304.8 1851.28   343.6 1852.44  348.661851.416     354 1850.25
   364.4 1851.25   367.2 1851.68   450.4 1851.24   514.7  1851.6   561.2 1852.86
   600.2 1855.41   623.5 1853.81   653.8 1853.56   825.7 1855.62   904.5 1855.54
  1091.6 1856.97  1117.9 1858.11  1140.9 1861.32  1167.1  1871.2  1182.5 1878.25
#Mann= 7 ,-1 , 0
       0      .1       0     100    .035       0  348.66    .045       0
   364.4    .035       0  554.75     .04       0  786.83    .035       0
 1176.83     .07       0
#XS Ineff= 2 , 0
          182.23 1853.88  491.69         1853.94
Permanent Ineff=
       F       F
Bank Sta=348.66,364.4
XS Rating Curve= 0 ,0
Exp/Cntr(USF)=0,0
Exp/Cntr=0.3,0.1

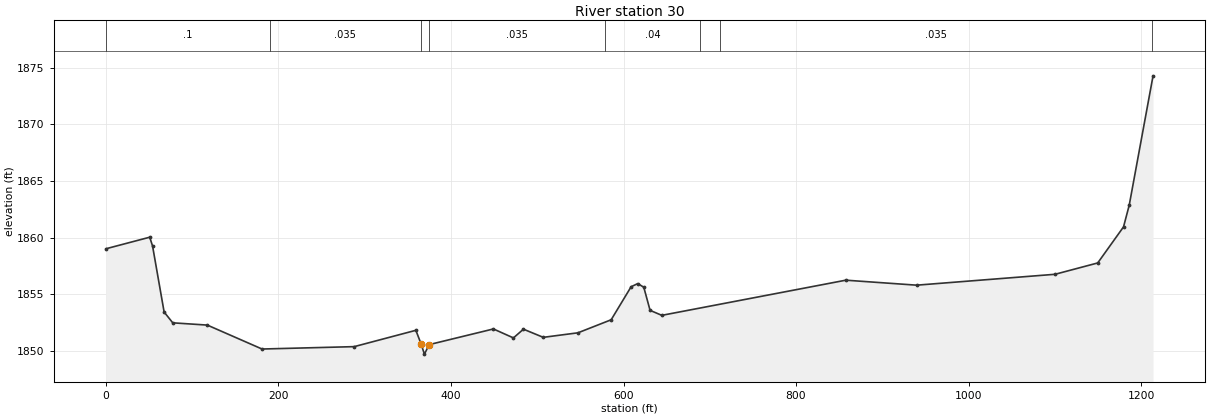
Type RM Length L Ch R = 1 ,30      ,,,
XS GIS Cut Line= 4
2054171.23505975157200.6834567892054224.83546568157484.598106978
 2054493.6750017157785.2628840222055014.60394689157811.225580646
#Sta/Elev= 30
       0 1859.02    50.8 1860.04    54.1 1859.26    67.5 1853.44    77.5 1852.49
   117.6 1852.29     181 1850.18   287.8 1850.39   359.3 1851.83  365.26 1850.65
   369.2 1849.73   374.8 1850.57   449.2 1851.95   472.4 1851.16     484 1851.93
     507 1851.21   547.2 1851.61   585.7 1852.76   608.8 1855.67   616.5 1855.95
   623.5 1855.63   630.8 1853.59   644.4 1853.15   857.7 1856.25   939.8 1855.81
  1100.2 1856.77  1149.7 1857.77  1179.6 1860.95  1186.2 1862.861213.834 1874.27
#Mann= 8 ,-1 , 0
       0      .1       0     190    .035       0  365.26    .045       0
   374.8    .035       0  578.93     .04       0  688.93     .06       0
  712.26    .035       0 1212.26     .07       0
Bank Sta=365.26,374.8
XS Rating Curve= 0 ,0
Exp/Cntr(USF)=0,0
Exp/Cntr=0.3,0.1
LCMann Table=0

Chan Stop Cuts=-1
Use User Specified Reach Order=0
Composite Channel Slope=5